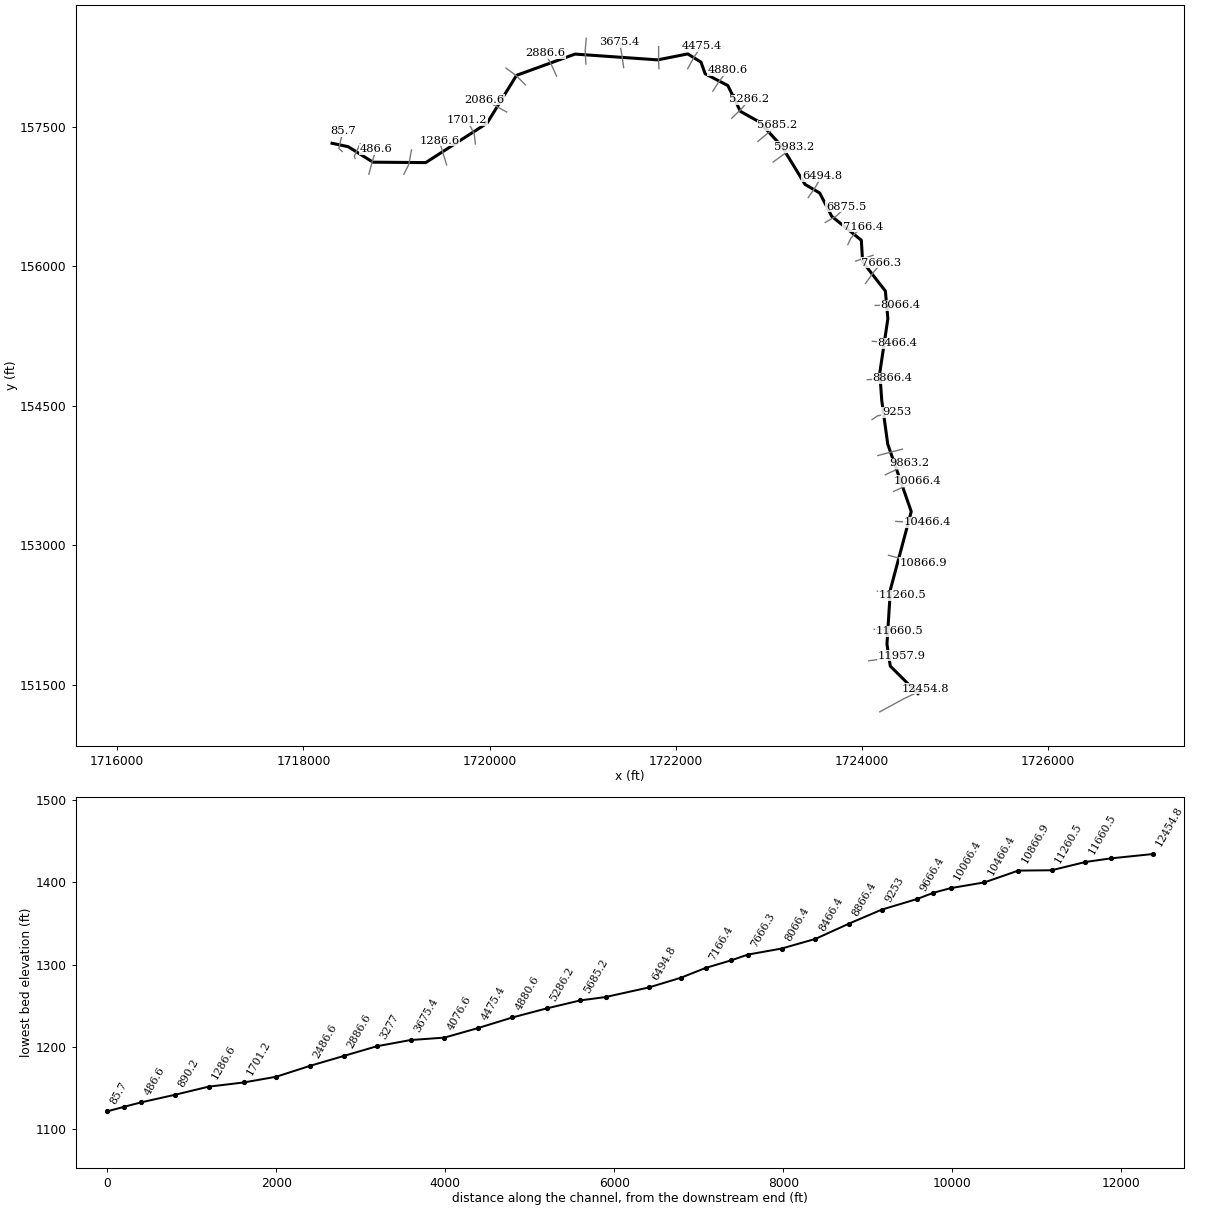
--- George Branch.prj (project) ---

Proj Title=George Branch
Current Plan=p01
Default Exp/Contr=0,0
English Units
Geom File=g01
Flow File=f01
Plan File=p01
BEGIN DESCRIPTION:
END DESCRIPTION:
DSS Export Rating Curves= 0
DSS Export Rating Curve Sorted= 0
DSS Export Volume Flow Curves= 0
DXF OffsetX= 0
DXF OffsetY= 0
DXF ScaleX= 0
DXF ScaleY= 0

--- George Branch.p01 (plan) ---

Plan Title=Floodplain
Program Version=4.00
Geom File=g01
Flow File=f01
K Sum by GR=0
Std Step Tol=0.01
Critical Tol=0.01
Num of Std Step Trials=20
Max Error Tol=0.3
Flow Tol Ratio=0.001
Split Flow NTrial=30
Split Flow Tol=0.02
Split Flow Ratio=0.02
Log Output Level=0
Friction Slope Method=1
Unsteady Friction Slope Method=2
Unsteady Bridges Friction Slope Method=1
Global Log Level=0
CheckData=False
Run HTab=0
Run UNet=0
Run PostProcess=0
UNET Theta=0
UNET Theta Warmup=0
UNET ZTol=0
UNET ZSATol=0
UNET MxIter=0
UNET MaxInSteps=0
UNET DtIC=0
UNET DtMin=0
UNET MaxCRTS=0
UNET WFStab=0
UNET SFStab=0
UNET WFX=0
UNET SFX=0
UNET DSS MLevel=0
UNET DZMax Abort=0
UNET Convert EG Bridges=0
UNET Use Existing IB Tables=0
UNET Froude Limit=0
UNET Froude Power=0
Write IC File=0
Echo Input=False
Echo Output=False
Write Detailed=0

--- George Branch.f01 (steady flow) ---

Flow Title=NFF Regression Equation
Program Version=4.00
Number of Profiles=1
Profile Names=P100yr
River Rch & RM=George Branch,Main      ,12454.8
611.8405
River Rch & RM=George Branch,Main      ,11957.9
653.1125
River Rch & RM=George Branch,Main      ,10066.4
707.3080
River Rch & RM=George Branch,Main      ,7666.3
772.4997
River Rch & RM=George Branch,Main      ,5983.2
856.6311
River Rch & RM=George Branch,Main      ,5685.2
890.2150
River Rch & RM=George Branch,Main      ,3277
974.0668
River Rch & RM=George Branch,Main      ,284.1
1071.724
Boundary for River Rch & Prof#=George Branch,Main      ,1
Up Type=0
Dn Type=3
Dn Slope=0.026736

--- George Branch.g01 (geometry) ---

Geom Title=Geometry
Program Version=4.00

River Reach=George Branch   ,Main
Reach XY= 30
      1724601.53      151408.613     1724303.963      151704.275
     1724268.116      151940.701     1724305.187      152526.307
     1724529.013      153364.436     1724276.583      154088.336
     1724212.474      154555.799     1724191.104      154854.308
     1724277.919      155435.965     1724251.206      155733.137
      1724006.79      156047.006     1723992.766      156278.733
     1723674.903      156535.518     1723545.598      156786.049
     1723389.016      156877.977     1723137.977      157288.453
     1722900.079       157547.74     1722693.998      157662.903
     1722559.659      157939.562     1722315.242      158067.113
       1722270.5      158191.992     1722128.257      158280.142
     1721806.376      158216.033     1720918.064      158278.116
     1720289.125       158049.75     1719972.001       157535.29
     1719313.881       157112.57     1718747.416      157117.078
     1718480.461      157283.862     1718307.398      157320.109

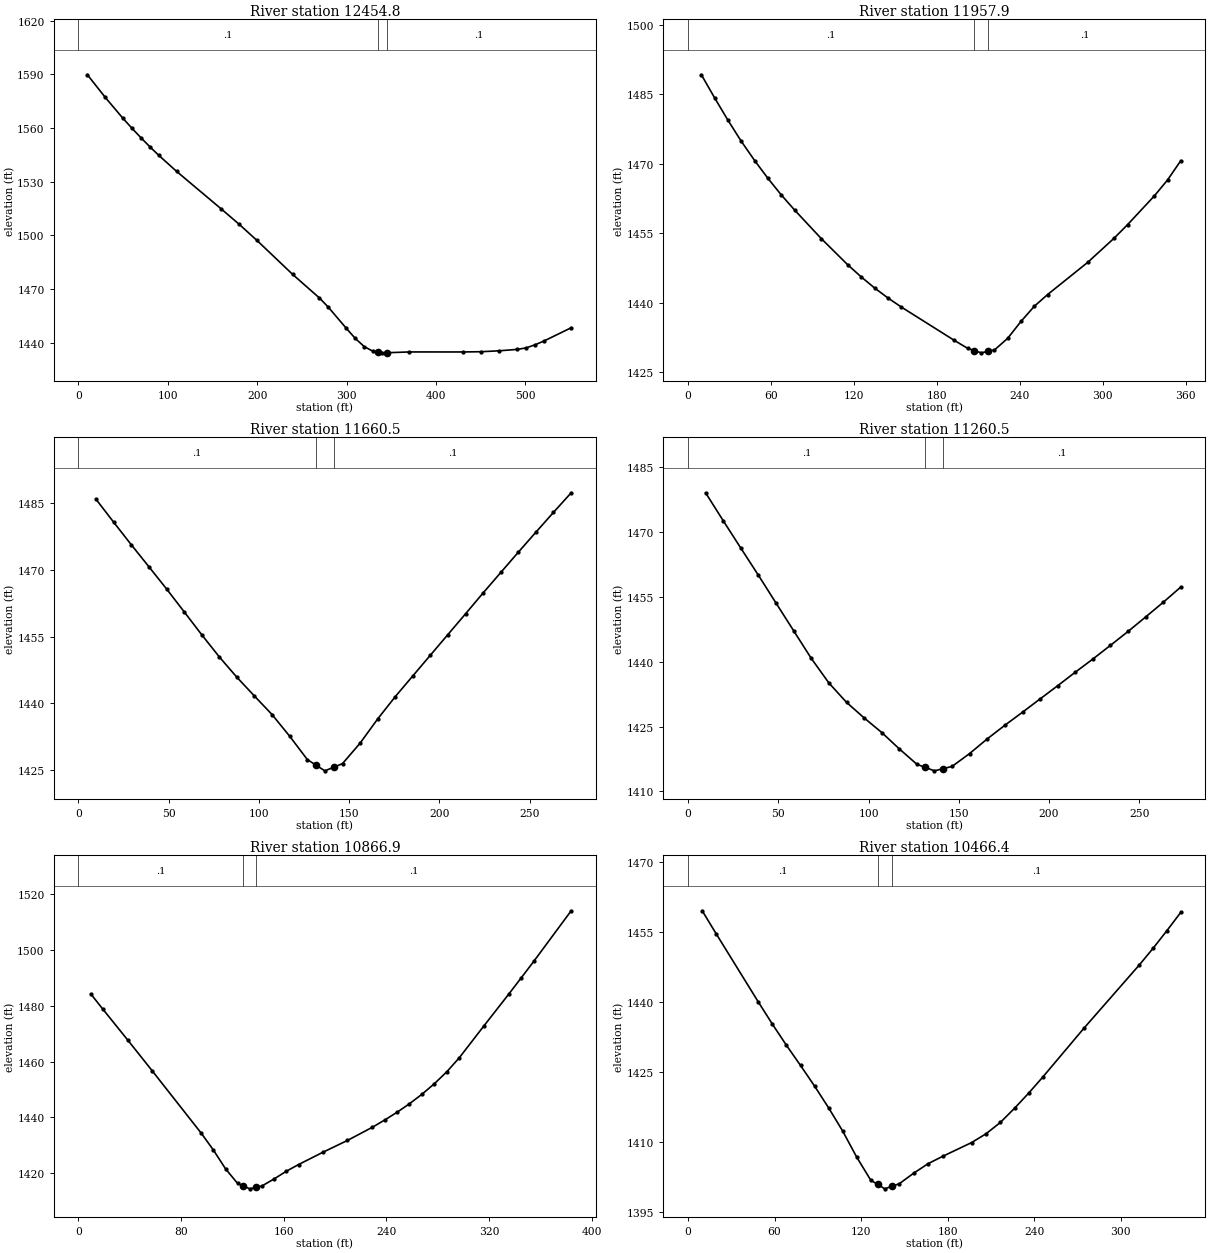
Type RM Length L Ch R = 1 ,12454.8 ,502.8,497,491.1
XS GIS Cut Line= 3
      1724190.59      151212.912     1724453.681      151356.416
     1724681.569      151463.204
#Sta/Elev= 30
      10  1589.8      30 1577.14    49.9 1565.39    59.9 1559.88    69.9 1554.61
    79.9 1549.57    89.9 1544.76   109.9 1535.77   159.8 1514.82   179.8 1506.27
   199.8  1497.2   239.7 1478.24   269.7 1465.05   279.7 1459.88   299.7 1448.13
   309.8 1442.45   319.8  1437.9   329.9 1435.17     335 1434.79     340 1434.41
     345 1434.46   370.2 1434.91   430.6  1434.9   450.7 1435.04   470.8 1435.55
     491 1436.33     501 1437.17   511.1 1438.93   521.2 1441.08   551.4 1448.43
#Mann= 3 , 0 , 0
       0      .1       0     335    .045       0     345      .1       0
Bank Sta=335,345
XS Rating Curve= 0 ,0
Exp/Cntr=0.3,0.1

Type RM Length L Ch R = 1 ,11957.9 ,302.4,297.3,292.3
XS GIS Cut Line= 3
     1724072.407      151761.419     1724244.177      151785.336
     1724424.645      151815.777
#Sta/Elev= 30
     9.6 1489.25    19.3  1484.2    28.9 1479.39    38.5 1474.86    48.2 1470.68
    57.8 1466.84    67.4 1463.28    77.1 1459.99    96.3 1453.85   115.6 1448.14
   125.3 1445.54   134.9 1443.16   144.5 1441.02   154.2 1439.05   192.7 1431.81
   202.3  1430.1     207 1429.63     212 1429.14     217 1429.46   221.6 1429.75
   231.2 1432.29   240.9 1435.96   250.5 1439.22   260.1 1441.75     289 1448.68
   308.3 1453.96   317.9 1456.85   337.2 1463.04   346.8  1466.5   356.4 1470.68
#Mann= 3 , 0 , 0
       0      .1       0     207    .045       0     217      .1       0
Bank Sta=207,217
XS Rating Curve= 0 ,0
Exp/Cntr=0.3,0.1

Type RM Length L Ch R = 1 ,11660.5 ,401.7,400,398.3
XS GIS Cut Line= 3
     1724131.248       152099.93     1724267.246      152088.231
     1724403.243      152076.533
#Sta/Elev= 30
     9.8 1485.88    19.5 1480.75    29.2 1475.71      39 1470.74    48.8 1465.74
    58.5 1460.62    68.2 1455.47      78 1450.45    87.8 1445.84    97.5 1441.63
   107.3 1437.44     117 1432.59   126.8 1427.33   131.5  1426.1   136.5 1424.79
   141.5 1425.62   146.3 1426.42     156    1431   165.8 1436.48   175.5 1441.48
   185.3 1446.18     195 1450.83   204.7 1455.47   214.5 1460.15   224.2 1464.83
     234 1469.44   243.7    1474   253.5 1478.53   263.2 1482.97     273 1487.38
#Mann= 3 , 0 , 0
       0      .1       0   131.5    .045       0   141.5      .1       0
Bank Sta=131.5,141.5
XS Rating Curve= 0 ,0
Exp/Cntr=0.3,0.1

Type RM Length L Ch R = 1 ,11260.5 ,395.1,393.6,392.1
XS GIS Cut Line= 3
     1724163.766      152509.633     1724298.263      152486.335
      1724432.76      152463.036
#Sta/Elev= 30
     9.7 1479.03    19.5 1472.55    29.2 1466.25      39 1459.94    48.7 1453.55
    58.5 1447.13    68.2 1440.78      78 1435.07    87.8 1430.58    97.5    1427
   107.3 1423.61     117 1419.84   126.8 1416.26   131.5 1415.53   136.5 1414.75
   141.5 1415.27   146.3 1415.78     156 1418.75   165.8 1422.15   175.5 1425.28
   185.3  1428.3     195 1431.36   204.8 1434.43   214.5 1437.54   224.3  1440.6
     234 1443.75   243.8 1446.98   253.5 1450.31   263.3 1453.72     273 1457.24
#Mann= 3 , 0 , 0
       0      .1       0   131.5    .045       0   141.5      .1       0
Bank Sta=131.5,141.5
XS Rating Curve= 0 ,0
Exp/Cntr=0.3,0.1

Type RM Length L Ch R = 1 ,10866.9 ,396.8,400.5,404.3
XS GIS Cut Line= 4
     1724284.986       152894.83     1724368.113      152872.491
     1724487.837      152842.585      1724659.47      152811.611
#Sta/Elev= 30
     9.6 1484.26    19.1 1478.73    38.3 1467.76    57.4  1456.7    95.6 1434.33
   105.1 1428.26   114.6 1421.51     124 1416.26   128.5 1415.35   133.5 1414.33
   138.5 1414.88     143 1415.37   152.5 1417.91     162 1420.66   171.5 1423.05
   190.5 1427.47   209.5 1431.68   228.9  1436.4   238.5    1439   248.2  1441.8
   257.9 1444.86   267.6 1448.26   277.3 1452.05     287 1456.34   296.7 1461.35
   316.1 1472.91   335.4 1484.28   345.1 1490.11   354.8 1495.98   383.9  1514.1
#Mann= 3 , 0 , 0
       0      .1       0   128.5    .045       0   138.5      .1       0
Bank Sta=128.5,138.5
XS Rating Curve= 0 ,0
Exp/Cntr=0.3,0.1

Type RM Length L Ch R = 1 ,10466.4 ,390.3,400,409.7
XS GIS Cut Line= 4
     1724363.756      153258.857      1724500.02      153250.835
     1724590.093      153245.532     1724705.131      153248.647
#Sta/Elev= 29
     9.8 1459.49    19.5 1454.56    48.7 1439.99    58.5 1435.23    68.2 1430.73
      78  1426.4    87.8 1421.96    97.5 1417.33   107.2 1412.39     117 1406.78
   126.7 1401.87   131.5 1400.96   136.5 1400.01   141.5 1400.56   146.5  1401.1
   156.6 1403.38   166.6 1405.41   176.6 1406.96   196.7 1409.91   206.7 1411.79
   216.7 1414.23   226.7 1417.32   236.3 1420.49   245.9 1423.86   274.7  1434.4
     313 1447.89   322.6 1451.47   332.2 1455.25   341.8 1459.15
#Mann= 3 , 0 , 0
       0      .1       0   131.5    .045       0   141.5      .1       0
Bank Sta=131.5,141.5
XS Rating Curve= 0 ,0
Exp/Cntr=0.3,0.1

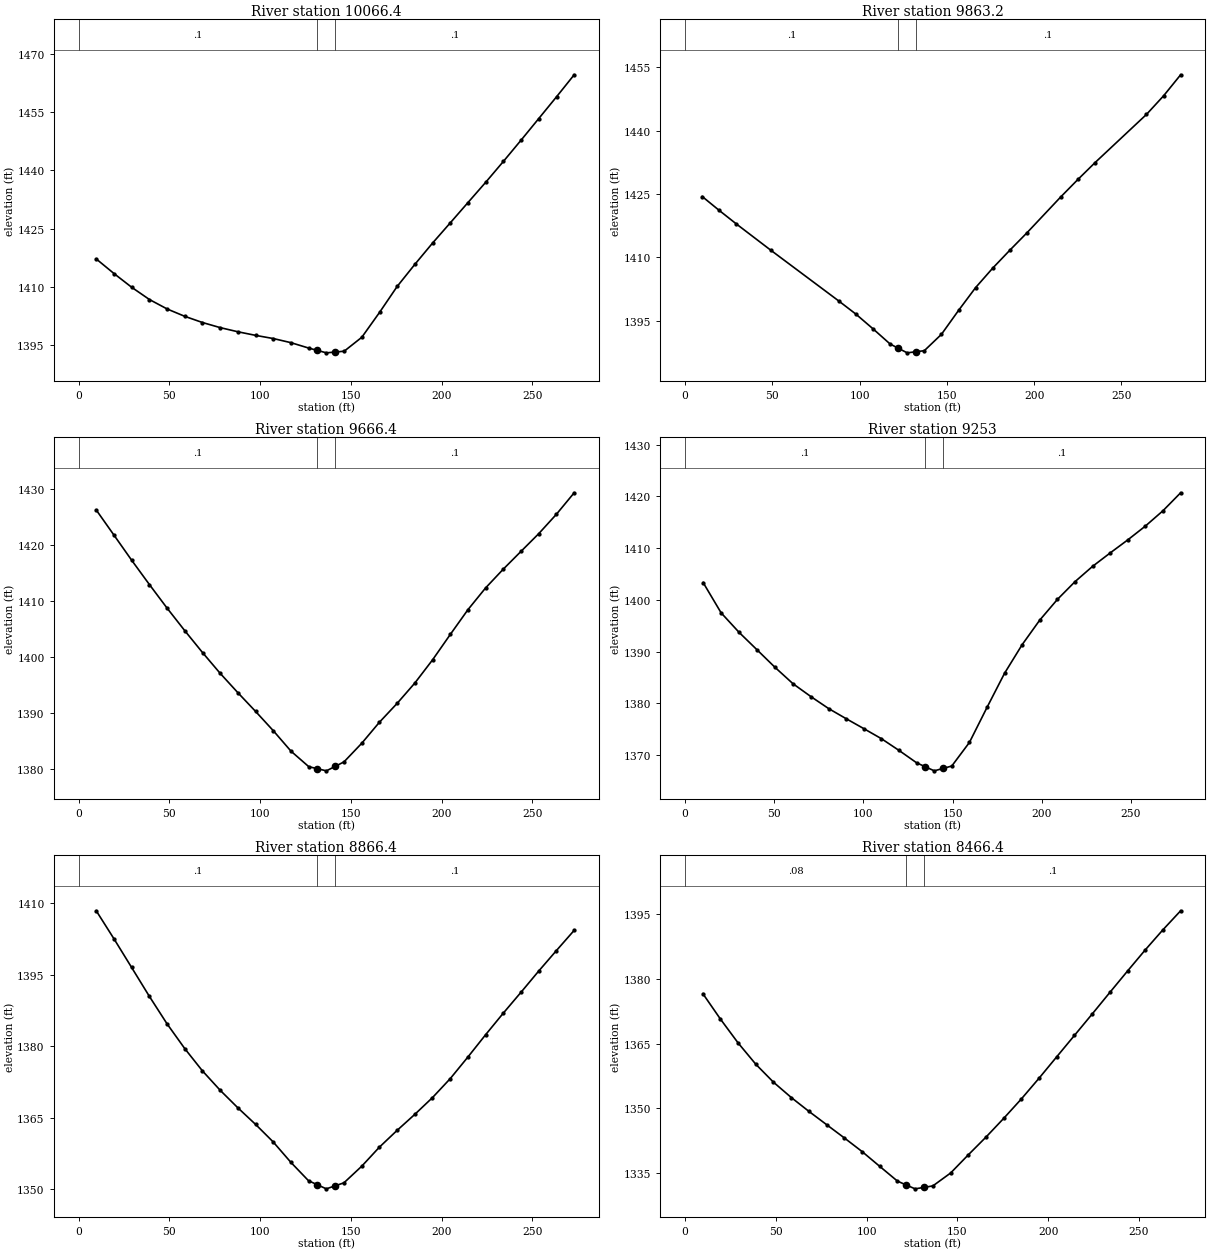
Type RM Length L Ch R = 1 ,10066.4 ,202.7,203.2,203.7
XS GIS Cut Line= 3
      1724340.46      153581.171     1724465.096      153636.833
     1724589.731      153692.496
#Sta/Elev= 30
     9.7 1417.18    19.5 1413.42    29.3 1409.87      39 1406.75    48.8 1404.31
    58.5 1402.42    68.2 1400.84      78 1399.52    87.8 1398.45    97.5 1397.53
   107.3 1396.71     117 1395.65   126.8 1394.26   131.5 1393.67   136.5 1393.04
   141.5 1393.25   146.3 1393.46     156 1397.04   165.8 1403.45   175.5 1410.12
   185.3 1415.83     195 1421.27   204.8 1426.49   214.5 1431.68   224.3 1436.91
     234 1442.25   243.8 1447.75   253.5 1453.28   263.3 1458.88     273 1464.53
#Mann= 3 , 0 , 0
       0      .1       0   131.5    .045       0   141.5      .1       0
Bank Sta=131.5,141.5
XS Rating Curve= 0 ,0
Exp/Cntr=0.3,0.1

Type RM Length L Ch R = 1 ,9863.2  ,200.6,196.8,193
XS GIS Cut Line= 2
       1724250.7       153759.61     1724507.268      153881.371
#Sta/Elev= 24
     9.8 1424.43    19.6 1421.12    29.4 1417.92      49 1411.74    88.1 1399.67
    97.9 1396.56   107.7 1393.08   117.5 1389.48   122.3 1388.45   127.3 1387.39
   132.3 1387.65   137.1  1387.9   146.9 1391.77   156.7 1397.43   166.5 1402.85
   176.3 1407.46   186.1  1411.7   195.9 1415.82   215.4 1424.38   225.2  1428.5
     235 1432.48   264.4 1443.87   274.2 1448.27     284 1453.27
#Mann= 3 , 0 , 0
       0      .1       0   122.3    .045       0   132.3      .1       0
Bank Sta=122.3,132.3
XS Rating Curve= 0 ,0
Exp/Cntr=0.3,0.1

Type RM Length L Ch R = 1 ,9666.4  ,414.8,413.4,412
XS GIS Cut Line= 3
     1724170.136      153966.235     1724302.243      154000.584
     1724434.351      154034.932
#Sta/Elev= 30
     9.7 1426.26    19.5 1421.76    29.2  1417.3      39 1412.95    48.7 1408.76
    58.5 1404.71    68.3  1400.8      78  1397.1    87.8 1393.63    97.5 1390.31
   107.3 1386.85     117 1383.22   126.8 1380.45   131.5 1380.09   136.5 1379.71
   141.5 1380.53   146.2 1381.31     156 1384.64   165.7 1388.38   175.5 1391.76
   185.2 1395.37     195 1399.52   204.8 1404.07   214.5 1408.48   224.2 1412.35
     234 1415.72   243.7 1418.87   253.5 1422.04   263.2 1425.49     273 1429.33
#Mann= 3 , 0 , 0
       0      .1       0   131.5    .045       0   141.5      .1       0
Bank Sta=131.5,141.5
XS Rating Curve= 0 ,0
Exp/Cntr=0.3,0.1

Type RM Length L Ch R = 1 ,9253    ,389.4,386.6,384.1
XS GIS Cut Line= 3
     1724108.085      154351.775     1724165.902      154392.334
     1724369.469      154430.604
#Sta/Elev= 30
    10.1 1403.35    20.2 1397.49    30.3 1393.71    40.4 1390.33    50.4 1386.97
    60.5  1383.8    70.6  1381.3    80.5    1379    90.4 1377.03   100.2 1375.13
   110.1 1373.18   119.9 1370.93   129.8 1368.53   134.7 1367.76   139.7 1366.98
   144.7 1367.45   149.5 1367.91   159.4 1372.47   169.3 1379.26   179.1 1385.83
     189 1391.37   198.8 1396.08   208.7 1400.08   218.6 1403.52   228.4 1406.46
   238.3 1409.06   248.2 1411.59     258 1414.24   267.9 1417.21   277.8 1420.68
#Mann= 3 , 0 , 0
       0      .1       0   134.7    .045       0   144.7      .1       0
Bank Sta=134.7,144.7
XS Rating Curve= 0 ,0
Exp/Cntr=0.3,0.1

Type RM Length L Ch R = 1 ,8866.4  ,402.5,400,397.1
XS GIS Cut Line= 3
       1724056.8       154781.14     1724193.104       154787.65
     1724329.423      154796.413
#Sta/Elev= 30
     9.7 1408.41    19.5 1402.51    29.2 1396.51      39 1390.43    48.7 1384.69
    58.5 1379.47    68.2 1374.81      78 1370.73    87.7 1367.06    97.5 1363.57
   107.2 1359.89     117 1355.58   126.7 1351.73   131.5  1350.9   136.5 1350.03
   141.5 1350.68   146.2 1351.29     156 1354.77   165.7 1358.76   175.5  1362.3
   185.2 1365.64     195 1369.18   204.8 1373.17   214.5 1377.69   224.3 1382.39
     234  1386.9   243.8  1391.3   253.5 1395.73   263.3 1400.05   273.1  1404.3
#Mann= 3 , 0 , 0
       0      .1       0   131.5    .045       0   141.5      .1       0
Bank Sta=131.5,141.5
XS Rating Curve= 0 ,0
Exp/Cntr=0.3,0.1

Type RM Length L Ch R = 1 ,8466.4  ,398.2,400,401.8
XS GIS Cut Line= 3
     1724110.778      155193.331     1724246.853      155182.558
     1724382.927      155171.786
#Sta/Elev= 30
     9.8  1376.6    19.5 1370.69    29.3 1365.12      39 1360.21    48.7 1356.06
    58.5 1352.51    68.2  1349.3      78  1346.2    87.8 1343.11    97.5 1339.97
   107.3 1336.51     117 1333.11   121.8 1332.22   126.7 1331.32   131.8 1331.67
   136.5    1332   146.3    1335     156  1339.2   165.8 1343.34   175.5 1347.66
   185.3  1352.2     195 1356.99   204.7 1361.94   214.5 1366.92   224.3  1371.9
     234 1376.89   243.8 1381.89   253.5 1386.76   263.2 1391.41     273 1395.84
#Mann= 3 , 0 , 0
       0     .08       0   121.8    .045       0   131.8      .1       0
Bank Sta=121.8,131.8
XS Rating Curve= 0 ,0
Exp/Cntr=0.3,0.1

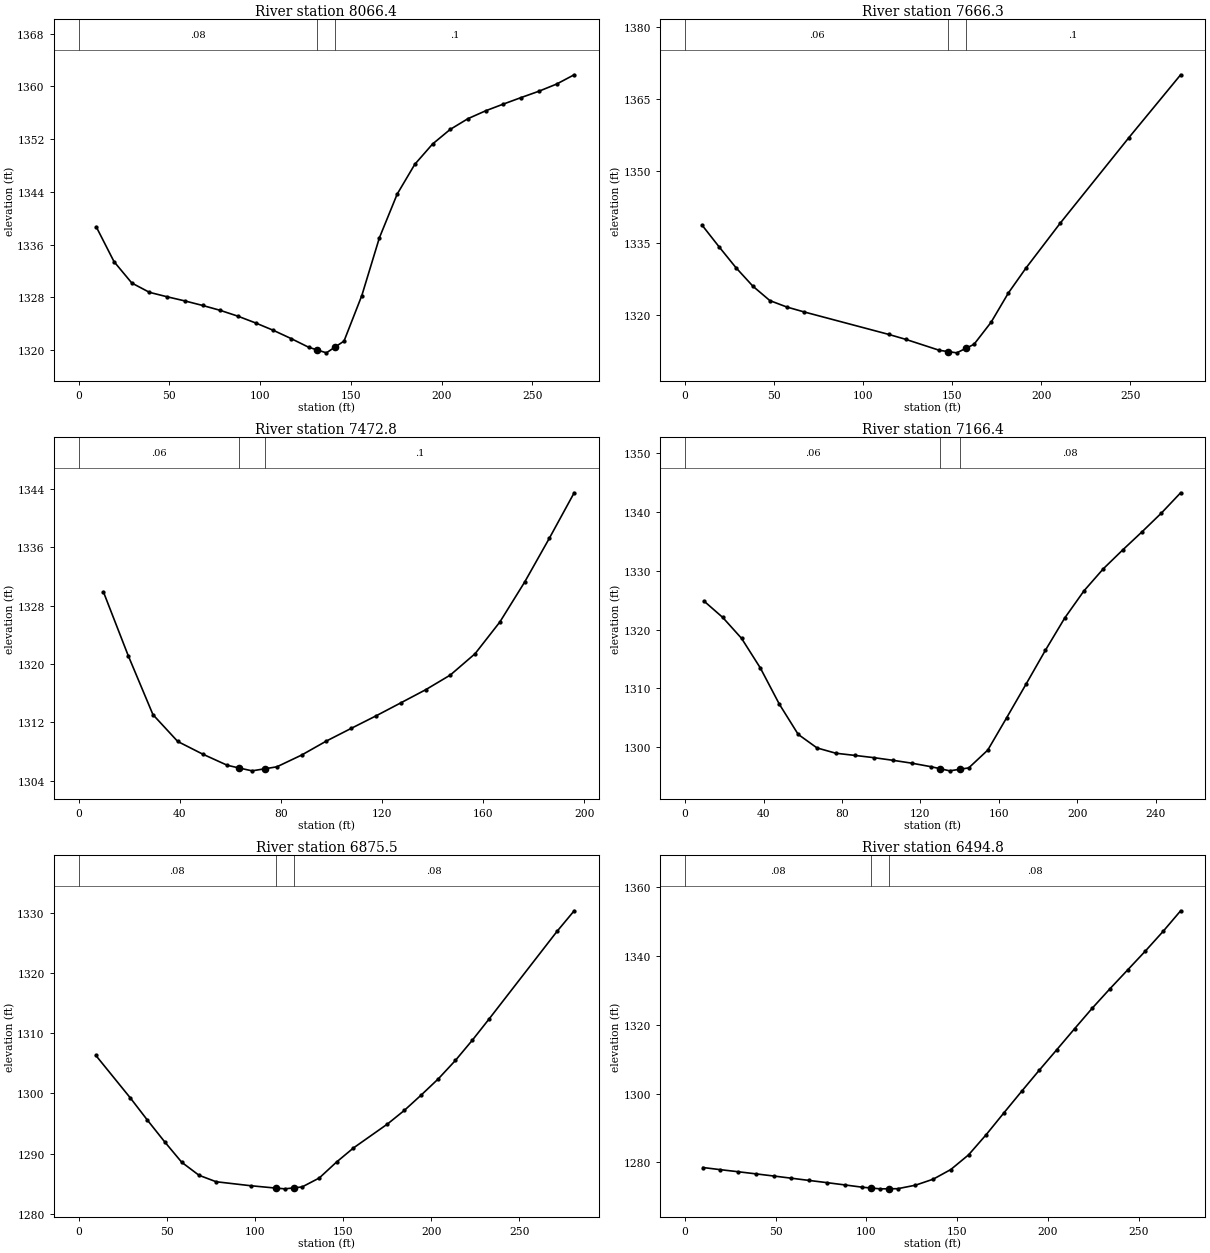
Type RM Length L Ch R = 1 ,8066.4  ,381,400.1,417.8
XS GIS Cut Line= 3
      1724141.84      155578.417     1724278.333      155579.769
     1724414.826       155581.12
#Sta/Elev= 30
     9.7 1338.71    19.5 1333.43    29.3 1330.19      39 1328.78    48.7 1328.11
    58.5 1327.48    68.3 1326.79      78 1326.05    87.7 1325.17    97.5 1324.14
   107.2 1323.03     117 1321.78   126.7 1320.46   131.5 1320.04   136.5 1319.61
   141.5 1320.53   146.2 1321.39     156 1328.28   165.7 1337.05   175.5 1343.67
   185.2 1348.18     195 1351.26   204.7 1353.47   214.5  1355.1   224.3  1356.3
     234 1357.31   243.7 1358.29   253.5 1359.25   263.3 1360.34     273 1361.75
#Mann= 3 , 0 , 0
       0     .08       0   131.5    .045       0   141.5      .1       0
Bank Sta=131.5,141.5
XS Rating Curve= 0 ,0
Exp/Cntr=0.3,0.1

Type RM Length L Ch R = 1 ,7666.3  ,206.1,193.5,182.2
XS GIS Cut Line= 3
      1724037.97      155814.843     1724120.783      155931.225
     1724206.657      156035.863
#Sta/Elev= 20
     9.5 1338.78      19  1334.3    28.6 1329.91    38.1 1326.07    47.6 1323.09
    57.1 1321.76    66.7 1320.75   114.3 1316.07   123.8 1315.05   142.8 1312.76
   147.5 1312.51   152.5 1312.24   157.5 1313.15   162.2 1314.01   171.8  1318.6
   181.5 1324.68   191.2 1329.77   210.5 1339.13   249.2 1356.97   278.2    1370
#Mann= 3 , 0 , 0
       0     .06       0   147.5    .045       0   157.5      .1       0
Bank Sta=147.5,157.5
XS Rating Curve= 0 ,0
Exp/Cntr=0.3,0.1

Type RM Length L Ch R = 1 ,7472.8  ,296.3,306.5,316.7
XS GIS Cut Line= 2
      1723932.91      156054.696     1724118.674      156117.196
#Sta/Elev= 22
     9.8 1329.88    19.6 1321.16    29.4 1313.07    39.2  1309.4      49 1307.68
    58.8 1306.14    63.6 1305.76    68.6 1305.38    73.6 1305.66    78.4 1305.93
    88.2 1307.54      98 1309.46   107.8 1311.19   117.6  1312.9   127.4 1314.68
   137.2 1316.47     147 1318.49   156.8 1321.41   166.6 1325.75   176.4 1331.21
   186.2 1337.23     196 1343.44
#Mann= 3 , 0 , 0
       0     .06       0    63.6    .045       0    73.6      .1       0
Bank Sta=63.6,73.6
XS Rating Curve= 0 ,0
Exp/Cntr=0.3,0.1

Type RM Length L Ch R = 1 ,7166.4  ,296.9,290.9,284.4
XS GIS Cut Line= 4
     1723847.841      156231.779     1723880.827      156301.224
     1723939.855       156365.46     1724007.563      156422.751
#Sta/Elev= 28
     9.6 1324.85    19.2 1322.06    28.8 1318.51    38.4 1313.47    48.1 1307.32
    57.7  1302.2    67.3  1299.9    76.9    1299    86.6 1298.63    96.3 1298.25
     106  1297.8   115.7 1297.31   125.3 1296.72     130 1296.38     135 1296.01
     140 1296.27   144.7 1296.51   154.4 1299.53   164.1 1305.06     174 1310.77
   183.8 1316.48   193.7 1321.98   203.5 1326.58   213.4 1330.34   223.2 1333.51
   233.1  1336.6     243 1339.79   252.8 1343.23
#Mann= 3 , 0 , 0
       0     .06       0     130    .045       0     140     .08       0
Bank Sta=130,140
XS Rating Curve= 0 ,0
Exp/Cntr=0.3,0.1

Type RM Length L Ch R = 1 ,6875.5  ,371.5,380.7,390.4
XS GIS Cut Line= 3
     1723605.194      156469.098     1723731.129      156543.543
     1723828.028      156637.213
#Sta/Elev= 24
     9.8  1306.3    29.3 1299.26      39 1295.57    48.8 1291.96    58.5 1288.56
    68.3  1286.4      78 1285.33    97.5 1284.67     112 1284.27     117 1284.15
     122 1284.31   126.8 1284.47   136.5 1285.95   146.3  1288.6   155.9 1290.94
   175.2 1294.92   184.8 1297.19   194.4 1299.75   204.1 1302.44   213.7 1305.47
   223.3 1308.83   232.9 1312.39   271.4 1326.93   281.1 1330.34
#Mann= 3 , 0 , 0
       0     .08       0     112    .045       0     122     .08       0
Bank Sta=112,122
XS Rating Curve= 0 ,0
Exp/Cntr=0.3,0.1

Type RM Length L Ch R = 1 ,6494.8  ,518.6,511.5,504.5
XS GIS Cut Line= 3
     1723422.618      156736.852     1723499.454      156849.989
     1723569.659      156966.997
#Sta/Elev= 30
     9.8 1278.51    19.5 1277.88    29.3 1277.28    39.1 1276.66    48.8 1276.04
    58.6  1275.4    68.4 1274.75    78.1 1274.12    87.9 1273.46    97.7 1272.78
   102.5 1272.55   107.5 1272.31   112.5 1272.33   117.2 1272.35     127 1273.37
   136.8 1275.12   146.5 1277.93   156.3  1282.2     166 1288.06   175.7 1294.36
   185.5 1300.64   195.2 1306.76     205 1312.81   214.7 1318.84   224.5 1324.85
   234.2 1330.46     244 1335.96   253.7 1341.41   263.5 1347.14   273.2 1353.15
#Mann= 3 , 0 , 0
       0     .08       0   102.5    .045       0   112.5     .08       0
Bank Sta=102.5,112.5
XS Rating Curve= 0 ,0
Exp/Cntr=0.3,0.1

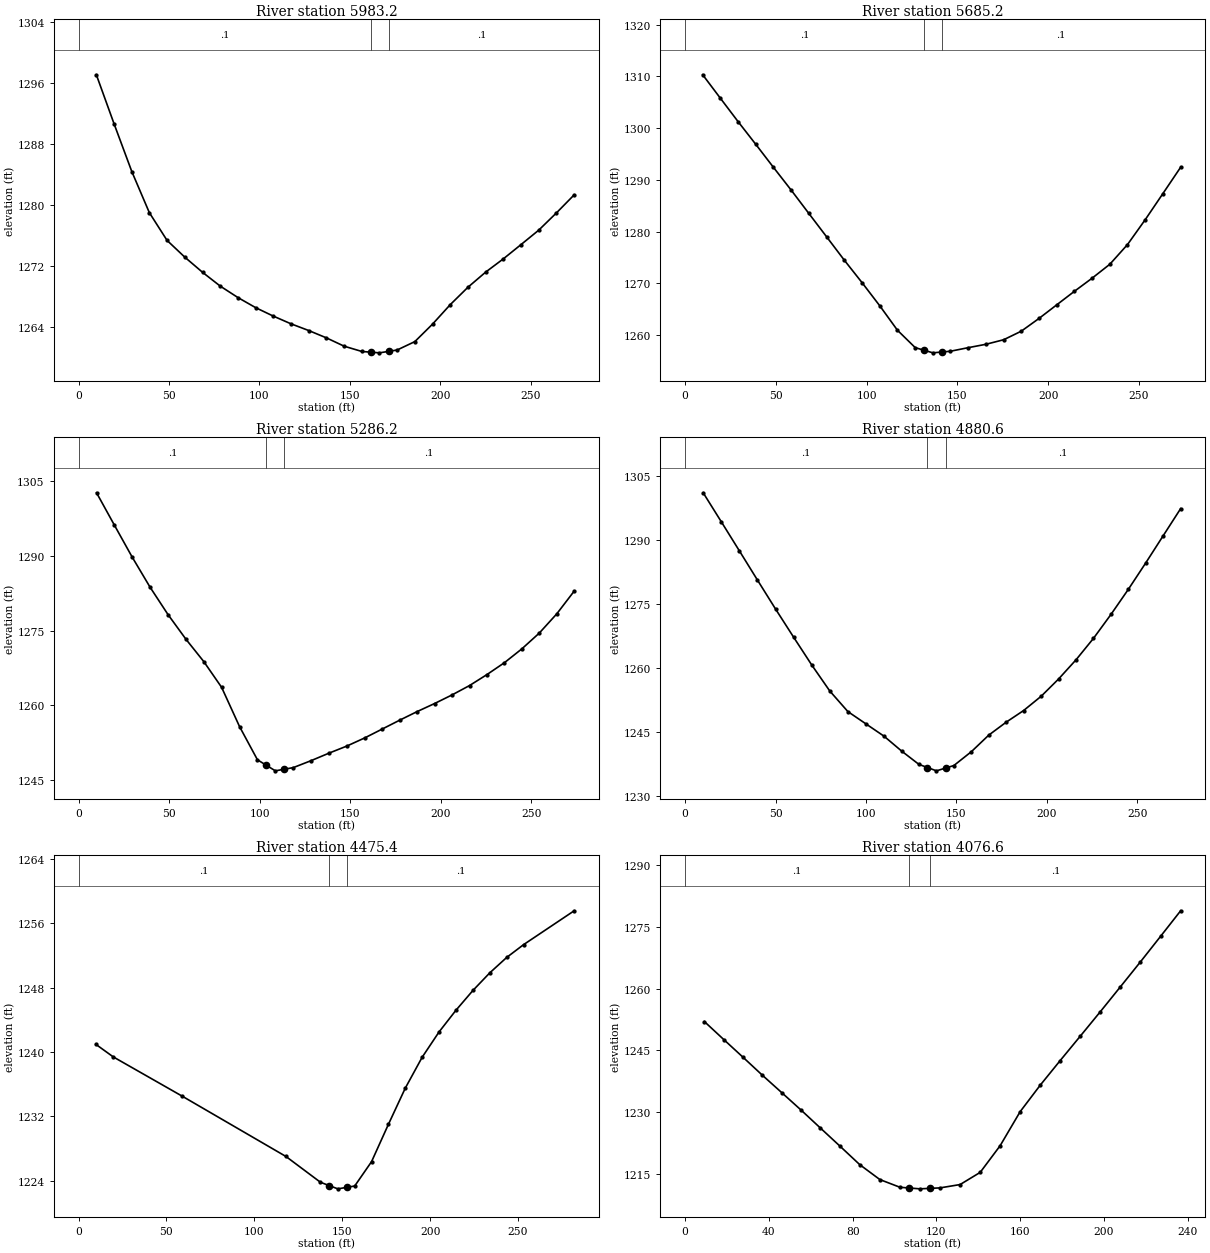
Type RM Length L Ch R = 1 ,5983.2  ,297,298.1,299.1
XS GIS Cut Line= 2
     1723045.548      157118.405     1723266.782      157280.037
#Sta/Elev= 30
     9.8 1297.06    19.6 1290.64    29.4  1284.4    39.1 1279.02    48.9 1275.39
    58.7  1273.2    68.5 1271.22    78.3 1269.41    88.1 1267.91    97.9 1266.59
   107.6 1265.49   117.4 1264.48   127.2  1263.6     137 1262.64   146.8 1261.55
   156.6 1260.86   161.4 1260.77   166.3 1260.68   171.4 1260.87   176.1 1261.05
   185.9 1262.15   195.7 1264.44   205.5 1266.99   215.3 1269.27   225.1 1271.25
   234.8 1272.97   244.6 1274.84   254.4 1276.73   264.2 1278.99     274 1281.35
#Mann= 3 , 0 , 0
       0      .1       0   161.4    .045       0   171.4      .1       0
Bank Sta=161.4,171.4
XS Rating Curve= 0 ,0
Exp/Cntr=0.3,0.1

Type RM Length L Ch R = 1 ,5685.2  ,397.6,399,400.5
XS GIS Cut Line= 3
     1722880.808      157339.791     1722986.253      157426.471
     1723091.699      157513.151
#Sta/Elev= 30
     9.7 1310.29    19.5 1305.73    29.2 1301.24      39 1296.83    48.7  1292.4
    58.5 1287.99    68.2  1283.5      78 1278.98    87.7 1274.49    97.5 1270.14
   107.3 1265.65     117 1260.95   126.8 1257.59   131.5 1257.11   136.5 1256.59
   141.5 1256.75   146.2  1256.9     156 1257.59   165.7 1258.24   175.5 1259.12
   185.2 1260.77     195 1263.24   204.7 1265.85   214.5 1268.48   224.2    1271
     234  1273.7   243.7 1277.49   253.5 1282.31   263.2 1287.33     273 1292.43
#Mann= 3 , 0 , 0
       0      .1       0   131.5    .045       0   141.5      .1       0
Bank Sta=131.5,141.5
XS Rating Curve= 0 ,0
Exp/Cntr=0.3,0.1

Type RM Length L Ch R = 1 ,5286.2  ,402.4,405.6,408.7
XS GIS Cut Line= 3
     1722599.905      157589.066     1722714.202       157698.26
     1722784.206      157790.467
#Sta/Elev= 30
     9.9 1302.73    19.8  1296.2    29.6  1289.8    39.5 1283.74    49.4 1278.25
    59.3  1273.3    69.2 1268.79      79 1263.64    88.9 1255.76    98.8 1249.08
   103.7 1247.98   108.7 1246.86   113.7 1247.19   118.6 1247.51   128.4  1248.9
   138.3 1250.41   148.2 1251.84   158.1 1253.48   167.7 1255.25   177.4 1257.04
     187 1258.76   196.7 1260.39   206.3 1262.11     216    1264   225.6  1266.2
   235.3  1268.6   244.9 1271.37   254.5 1274.53   264.2 1278.41   273.8 1282.97
#Mann= 3 , 0 , 0
       0      .1       0   103.7    .045       0   113.7      .1       0
Bank Sta=103.7,113.7
XS Rating Curve= 0 ,0
Exp/Cntr=0.3,0.1

Type RM Length L Ch R = 1 ,4880.6  ,402,405.2,406.5
XS GIS Cut Line= 3
     1722397.866      157879.983     1722456.601      157973.035
     1722556.576      158103.052
#Sta/Elev= 30
      10 1301.11      20 1294.32      30 1287.49      40 1280.63      50 1273.84
      60 1267.22      70 1260.71      80 1254.59      90 1249.76     100 1246.87
     110 1243.98   119.7  1240.5   129.3 1237.36     134 1236.63     139 1235.85
     144  1236.5   148.6 1237.09   158.3 1240.35   167.9 1244.23   177.6 1247.29
   187.2 1250.01   196.9 1253.36   206.5  1257.4   216.2 1261.93   225.8 1266.94
   235.5 1272.57   245.1 1278.46   254.8 1284.71   264.4 1291.06     274 1297.39
#Mann= 3 , 0 , 0
       0      .1       0     134    .045       0     144      .1       0
Bank Sta=134,144
XS Rating Curve= 0 ,0
Exp/Cntr=0.3,0.1

Type RM Length L Ch R = 1 ,4475.4  ,388.5,398.8,410.9
XS GIS Cut Line= 3
     1722128.051      158122.401     1722199.607      158251.342
      1722275.34      158362.573
#Sta/Elev= 20
     9.8 1240.95    19.7 1239.39      59  1234.5     118 1227.01   137.6 1223.81
   142.5  1223.4   147.5 1222.99   152.5 1223.17   157.1 1223.34   166.7 1226.37
   176.3 1231.01   185.9 1235.51   195.5 1239.35   205.1 1242.49   214.7 1245.18
   224.4 1247.65     234 1249.84   243.6 1251.75   253.2 1253.34     282 1257.55
#Mann= 3 , 0 , 0
       0      .1       0   142.5    .045       0   152.5      .1       0
Bank Sta=142.5,152.5
XS Rating Curve= 0 ,0
Exp/Cntr=0.3,0.1

Type RM Length L Ch R = 1 ,4076.6  ,398.5,401.2,404.7
XS GIS Cut Line= 3
     1721819.163      158121.535     1721815.123      158195.279
     1721815.943       158357.98
#Sta/Elev= 27
     9.2    1252    18.5 1247.61    27.7 1243.31    36.9 1238.96    46.2 1234.71
    55.4 1230.49    64.6 1226.14    73.9 1221.76    83.4 1217.24      93 1213.62
   102.6 1211.75   107.1 1211.57   112.1 1211.37   117.1 1211.49   121.7  1211.6
   131.3 1212.41   140.9 1215.37   150.4 1221.83     160 1230.13   169.6 1236.57
   179.1 1242.53   188.7 1248.46   198.3 1254.42   207.8 1260.41   217.4 1266.49
     227 1272.68   236.6  1278.9
#Mann= 3 , 0 , 0
       0      .1       0   107.1    .045       0   117.1      .1       0
Bank Sta=107.1,117.1
XS Rating Curve= 0 ,0
Exp/Cntr=0.3,0.1

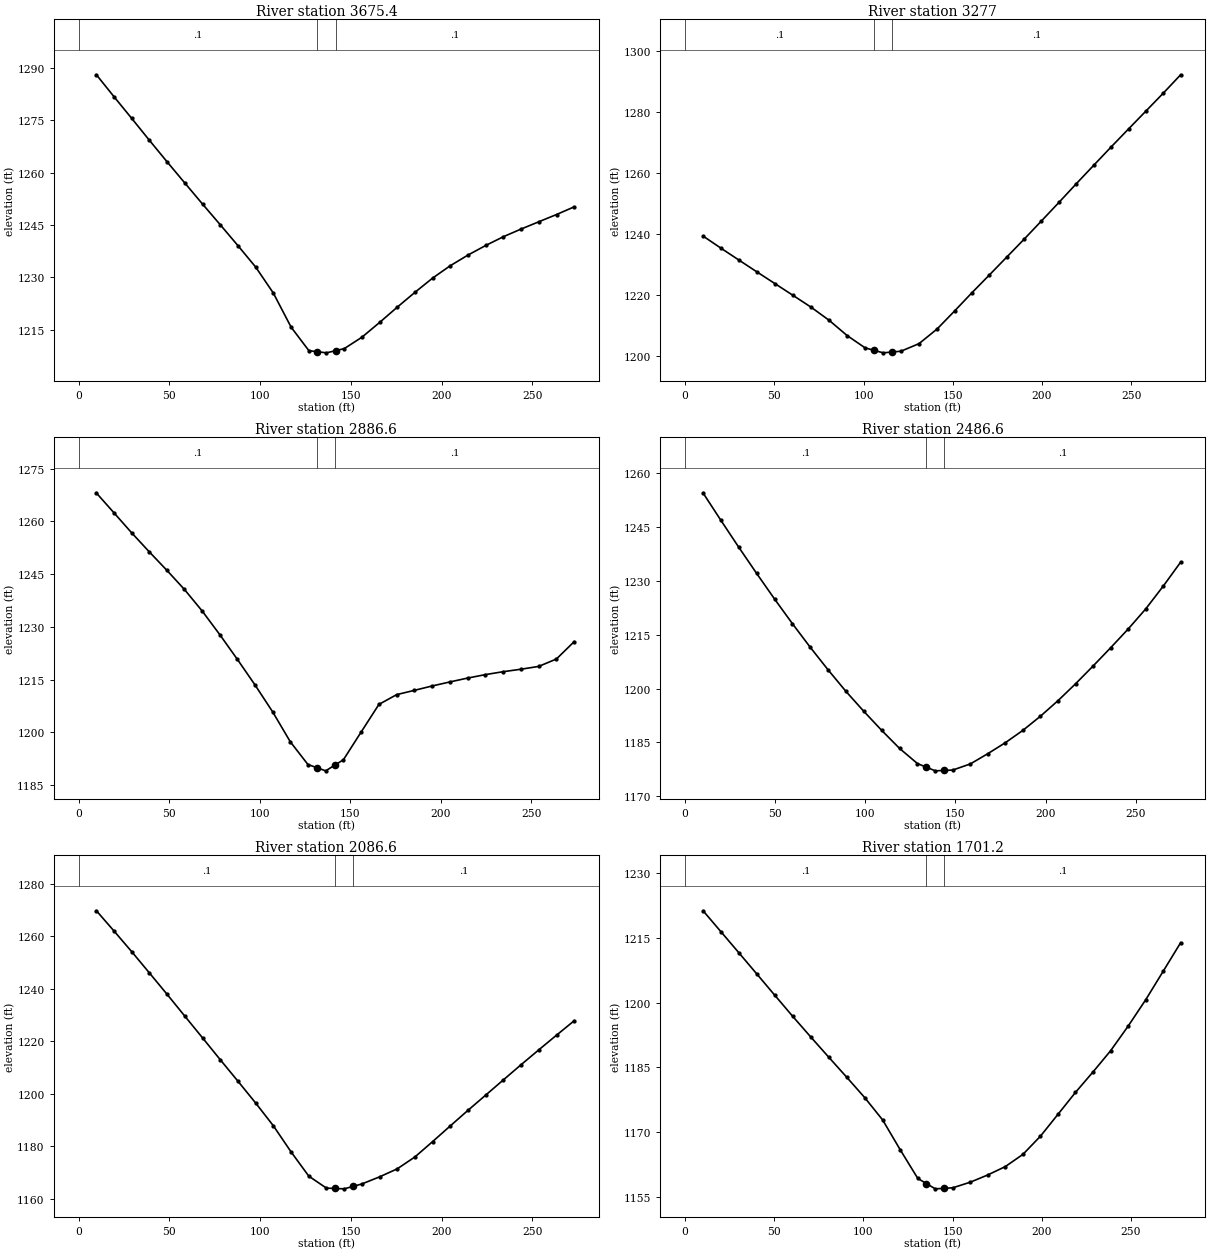
Type RM Length L Ch R = 1 ,3675.4  ,400.1,398.4,395.9
XS GIS Cut Line= 3
     1721439.967      158133.204     1721420.992      158268.502
     1721396.855      158402.829
#Sta/Elev= 30
     9.8 1287.98    19.5  1281.7    29.3 1275.47      39 1269.23    48.8 1263.04
    58.6 1256.96    68.3 1250.97    78.1 1245.03    87.8 1239.08    97.6 1232.93
   107.3 1225.51   117.1 1215.75   126.9 1209.02   131.6 1208.72   136.6  1208.4
   141.6 1209.02   146.4 1209.61   156.1 1212.86   165.9 1217.11   175.6 1221.47
   185.4 1225.74   195.1  1229.8   204.9 1233.36   214.6 1236.39   224.4 1239.14
   234.1 1241.64   243.9 1243.84   253.6 1245.91   263.4 1247.99   273.1 1250.18
#Mann= 3 , 0 , 0
       0      .1       0   131.6    .045       0   141.6      .1       0
Bank Sta=131.6,141.6
XS Rating Curve= 0 ,0
Exp/Cntr=0.3,0.1

Type RM Length L Ch R = 1 ,3277    ,382.9,390.4,399.2
XS GIS Cut Line= 3
     1721034.237      158171.035     1721026.843      158312.056
     1721037.815      158448.114
#Sta/Elev= 30
    10.1 1239.27    20.2 1235.26    30.3 1231.34    40.3 1227.48    50.4 1223.63
    60.5 1219.77    70.6 1215.89    80.7 1211.59    90.8 1206.56   100.9 1202.51
     106 1201.69     111 1200.88     116 1201.15     121 1201.42   131.1 1203.91
   141.2 1208.71     151 1214.63   160.7 1220.62   170.5 1226.48   180.2 1232.34
     190 1238.26   199.7 1244.26   209.5 1250.35   219.2 1256.48     229 1262.56
   238.7 1268.56   248.5 1274.51   258.2 1280.37     268  1286.3   277.7 1292.33
#Mann= 3 , 0 , 0
       0      .1       0     106    .045       0     116      .1       0
Bank Sta=106,116
XS Rating Curve= 0 ,0
Exp/Cntr=0.3,0.1

Type RM Length L Ch R = 1 ,2886.6  ,392.9,400,408.9
XS GIS Cut Line= 3
     1720719.758      158041.071     1720663.041      158165.078
     1720598.353      158286.065
#Sta/Elev= 30
     9.7 1268.15    19.5 1262.46    29.2 1256.81      39 1251.36    48.7 1246.12
    58.4 1240.67    68.2 1234.55    77.9 1227.84    87.7 1220.75    97.4  1213.5
   107.1 1205.88   116.9 1197.33   126.6 1190.89   131.4 1190.01   136.4 1189.09
   141.4  1190.7   146.2 1192.25     156 1200.14   165.8 1207.98   175.6 1210.76
   185.4 1211.98   195.2 1213.22     205 1214.37   214.8 1215.47   224.6 1216.45
   234.4 1217.28   244.2 1217.98     254 1218.78   263.8 1220.89   273.6 1225.82
#Mann= 3 , 0 , 0
       0      .1       0   131.4    .045       0   141.4      .1       0
Bank Sta=131.4,141.4
XS Rating Curve= 0 ,0
Exp/Cntr=0.3,0.1

Type RM Length L Ch R = 1 ,2486.6  ,394.1,400,402.5
XS GIS Cut Line= 3
     1720384.113       157947.55     1720286.568       158046.31
     1720177.341      158127.492
#Sta/Elev= 30
     9.9 1254.59    19.8 1246.95    29.7 1239.46    39.7  1232.1    49.6 1224.99
    59.5 1218.12    69.4 1211.53    79.3 1205.23    89.2 1199.23    99.2 1193.62
   109.1 1188.32     119  1183.3   128.9 1179.09   133.8 1178.08   138.8 1177.06
   143.8 1177.17   148.5 1177.28   158.3    1179     168 1181.87   177.7 1184.92
   187.4 1188.35   197.1 1192.28   206.9 1196.64   216.6 1201.33   226.3 1206.27
     236 1211.34   245.7 1216.55   255.5 1222.19   265.2 1228.53   274.9 1235.24
#Mann= 3 , 0 , 0
       0      .1       0   133.8    .045       0   143.8      .1       0
Bank Sta=133.8,143.8
XS Rating Curve= 0 ,0
Exp/Cntr=0.3,0.1

Type RM Length L Ch R = 1 ,2086.6  ,397.3,385.4,373.9
XS GIS Cut Line= 3
     1720183.394      157656.162     1720063.339      157721.156
     1719944.294      157787.937
#Sta/Elev= 30
     9.8 1269.77    19.5 1262.06    29.3 1254.14      39 1246.08    48.8 1237.88
    58.5 1229.62    68.3 1221.31      78 1213.04    87.8  1204.8    97.5 1196.54
   107.3 1187.82     117 1177.92   126.8 1168.65   136.5 1164.09   141.3 1163.95
   146.3 1163.81   151.3 1164.76     156 1165.66   165.8 1168.38   175.5 1171.42
   185.3 1175.98     195  1181.8   204.8 1187.82   214.5 1193.73   224.3 1199.55
     234 1205.33   243.8 1211.14   253.5 1216.77   263.3 1222.38     273 1227.86
#Mann= 3 , 0 , 0
       0      .1       0   141.3    .045       0   151.3      .1       0
Bank Sta=141.3,151.3
XS Rating Curve= 0 ,0
Exp/Cntr=0.3,0.1

Type RM Length L Ch R = 1 ,1701.2  ,418.4,414.6,410.7
XS GIS Cut Line= 3
     1719847.447      157312.347     1719835.128      157422.475
       1719757.1      157570.249
#Sta/Elev= 30
    10.1 1221.26    20.1 1216.41    30.2 1211.51    40.3 1206.58    50.4 1201.64
    60.4 1196.78    70.5 1192.01    80.6 1187.32    90.7 1182.67   100.7 1177.99
   110.8 1172.79   120.6 1165.92   130.5 1159.25   135.3 1158.07   140.3 1156.84
   145.3 1156.96   150.1 1157.08     160 1158.39   169.8 1160.07   179.6    1162
   189.5 1164.84   199.3 1169.05   209.1  1174.1   218.9 1179.17   228.8 1183.94
   238.6 1188.82   248.4  1194.5   258.3 1200.64   268.1 1207.24   277.9 1213.86
#Mann= 3 , 0 , 0
       0      .1       0   135.3    .045       0   145.3      .1       0
Bank Sta=135.3,145.3
XS Rating Curve= 0 ,0
Exp/Cntr=0.3,0.1

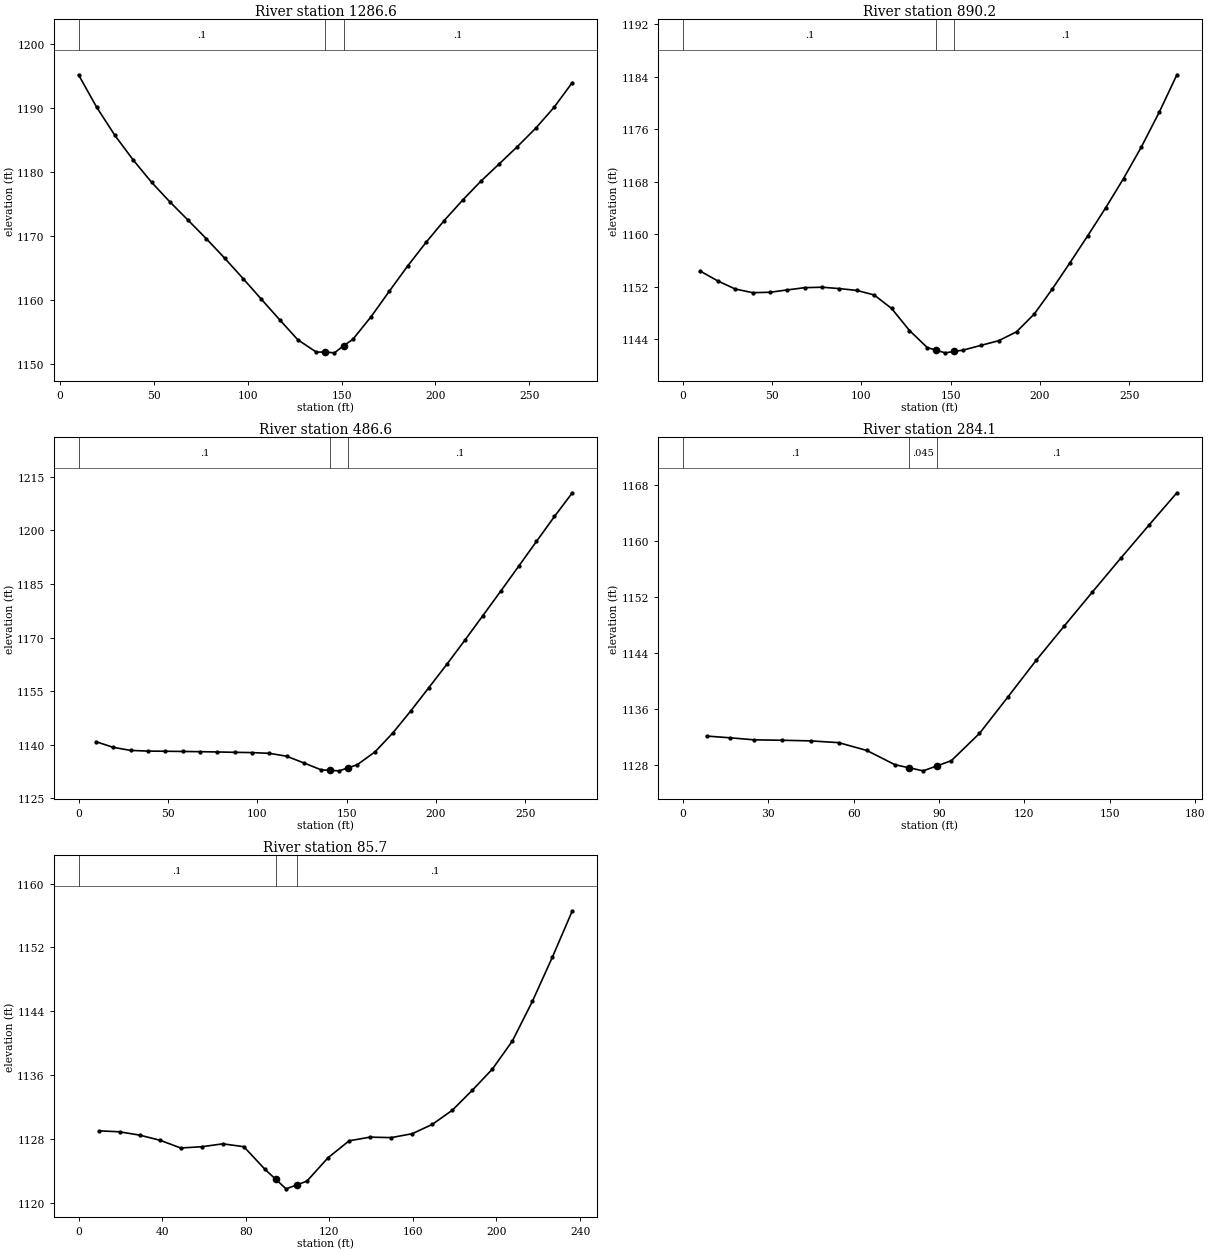
Type RM Length L Ch R = 1 ,1286.6  ,406.5,396.4,386.6
XS GIS Cut Line= 3
      1719538.51      157087.758     1719498.717      157218.329
     1719458.924        157348.9
#Sta/Elev= 30
     9.8 1195.23    19.5 1190.14    29.2 1185.74      39 1181.88    48.7 1178.43
    58.5 1175.35    68.3 1172.46      78 1169.57    87.7 1166.55    97.5 1163.37
   107.2 1160.15     117 1156.92   126.7 1153.79   136.5 1151.87   141.2 1151.87
  146.22 1151.75   151.2 1152.88     156 1153.86   165.7 1157.39   175.5 1161.41
   185.2 1165.32     195 1169.02   204.7 1172.44   214.5 1175.62   224.2 1178.58
     234 1181.29   243.7    1184   253.5 1186.88   263.2 1190.12     273 1194.02
#Mann= 3 , 0 , 0
     9.8      .1       0   141.2    .045       0   151.2      .1       0
Bank Sta=141.2,151.2
XS Rating Curve= 0 ,0
Exp/Cntr=0.3,0.1

Type RM Length L Ch R = 1 ,890.2   ,405.1,403.6,401.1
XS GIS Cut Line= 3
     1719079.446      156987.774     1719132.028      157092.139
     1719161.295      157249.426
#Sta/Elev= 30
     9.7 1154.38    19.5 1152.89    29.2 1151.67      39 1151.11    48.7 1151.17
    58.4 1151.53    68.2 1151.87    77.9 1151.94    87.6 1151.73    97.4 1151.45
   107.1 1150.76   116.9  1148.7   126.9 1145.35   136.9 1142.75   141.9 1142.35
   146.9 1141.95   151.9 1142.16   156.9 1142.36   166.9 1143.08   176.9  1143.8
   186.9 1145.15   196.9 1147.88   206.9 1151.65   216.9 1155.68   226.9 1159.81
   236.9 1164.04   246.9 1168.49   256.9  1173.3   266.9 1178.58   276.8 1184.28
#Mann= 3 , 0 , 0
       0      .1       0   141.9    .045       0   151.9      .1       0
Bank Sta=141.9,151.9
XS Rating Curve= 0 ,0
Exp/Cntr=0.3,0.1

Type RM Length L Ch R = 1 ,486.6   ,206.1,202.5,199.7
XS GIS Cut Line= 3
     1718703.056      156988.412     1718738.554      157119.478
     1718780.475      157253.618
#Sta/Elev= 30
     9.7 1140.83    19.4 1139.23    29.1 1138.38    38.8 1138.18    48.5 1138.14
    58.2 1138.08    67.9 1138.02    77.6 1137.94    87.3 1137.84      97 1137.76
   106.7 1137.56   116.4 1136.75   126.1 1134.86   135.8 1132.92   140.8 1132.78
   145.8 1132.65   150.8 1133.49   155.9 1134.35   165.9 1137.97   175.9 1143.29
     186 1149.51     196 1155.96   206.1 1162.51   216.1 1169.21   226.1 1176.05
   236.2 1182.98   246.2 1189.93   256.2 1196.91   266.3 1203.92   276.3 1210.56
#Mann= 3 , 0 , 0
       0      .1       0   140.8    .045       0   150.8      .1       0
Bank Sta=140.8,150.8
XS Rating Curve= 0 ,0
Exp/Cntr=0.3,0.1

Type RM Length L Ch R = 1 ,284.1   ,194,198.3,202.6
XS GIS Cut Line= 3
     1718555.203      157157.803     1718546.111      157181.037
     1718609.754      157315.394
#Sta/Elev= 20
     8.3 1132.18    16.6 1131.93      25 1131.64    34.9 1131.58    44.8 1131.49
    54.7 1131.24    64.6 1130.12    74.5 1128.08    79.4 1127.65    84.4 1127.21
    89.4 1127.94    94.3 1128.66   104.2 1132.56   114.2 1137.77   124.1 1142.99
     134 1147.91   143.9 1152.77   153.8 1157.57   163.7 1162.29   173.6 1166.95
#Mann= 3 , 0 , 0
       0      .1       0    79.4    .045       0    89.4      .1       0
Bank Sta=79.4,89.4
XS Rating Curve= 0 ,0
Exp/Cntr=0.3,0.1

Type RM Length L Ch R = 1 ,85.7    ,81.3,85.7,90.1
XS GIS Cut Line= 4
     1718416.805      157231.547     1718381.089      157264.972
     1718405.693      157372.975     1718426.667      157446.712
#Sta/Elev= 26
     9.8 1129.01    19.6 1128.89    29.3 1128.47    39.1 1127.82    48.9 1126.86
      59 1127.02    69.1 1127.38    79.1 1127.02    89.2 1124.19    94.3 1122.95
    99.3 1121.74   104.3 1122.22   109.3 1122.71   119.4 1125.64   129.5 1127.76
   139.5 1128.22   149.6 1128.16   159.7 1128.65   169.3 1129.82   178.9  1131.6
   188.4 1134.09     198 1136.74   207.6 1140.27   217.2 1145.25   226.8 1150.81
   236.3 1156.59
#Mann= 3 , 0 , 0
       0      .1       0    94.3    .045       0   104.3      .1       0
Bank Sta=94.3,104.3
XS Rating Curve= 0 ,0
Exp/Cntr=0.3,0.1

Chan Stop Cuts=-1
Use User Specified Reach Order=0